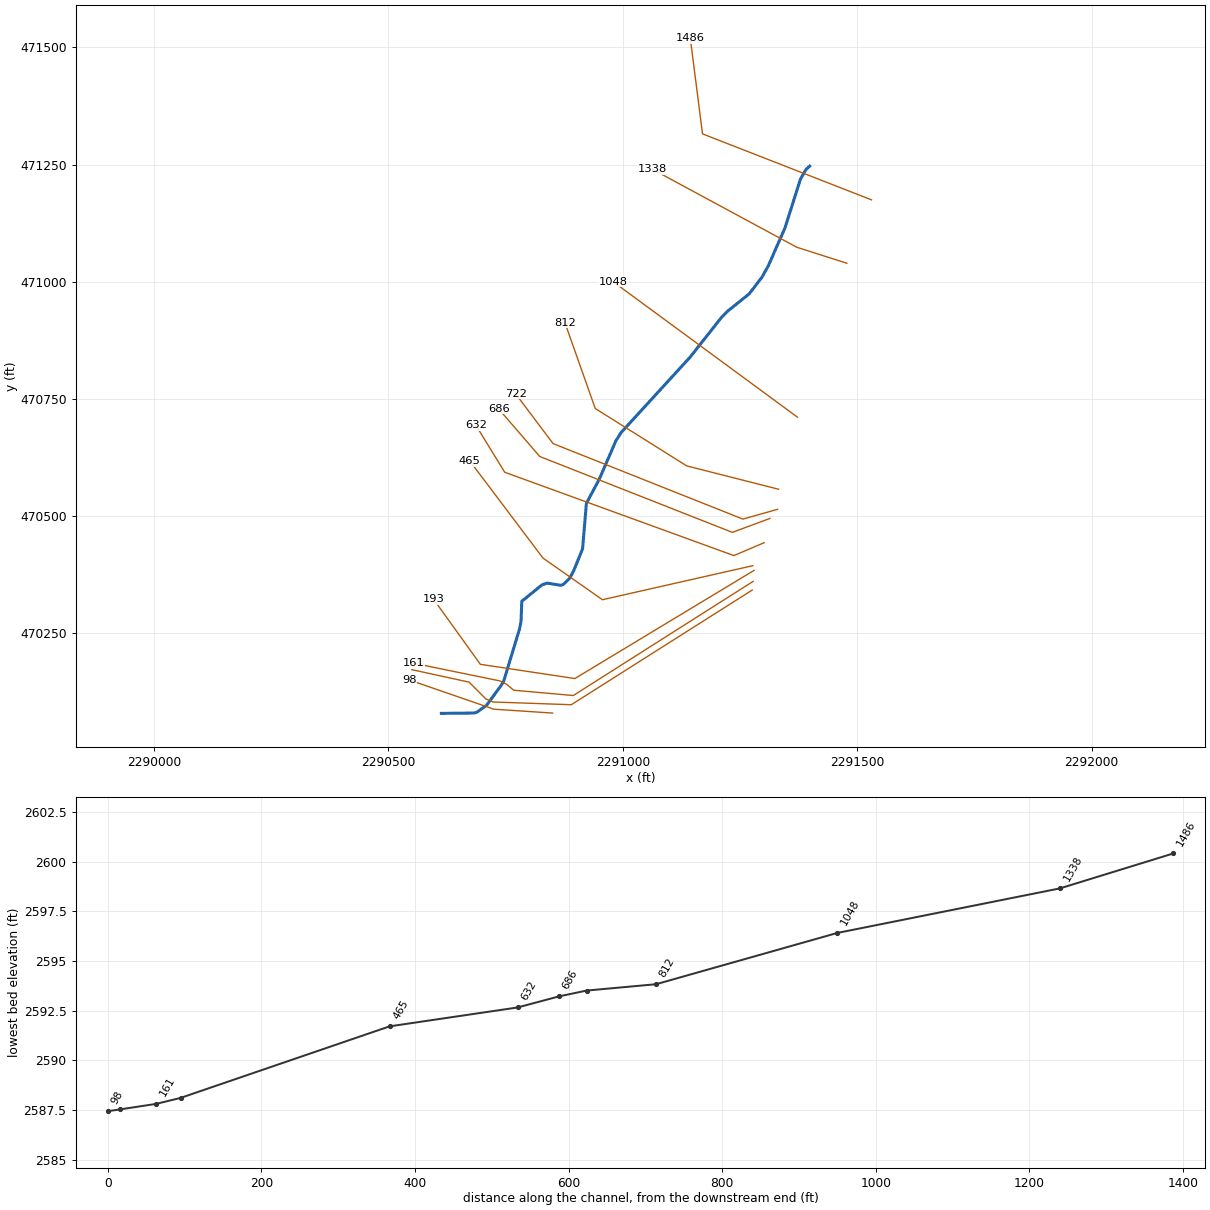
--- SGRCMPRNT1.prj (project) ---

Proj Title=SGRCMPRNT1
Current Plan=p01
Default Exp/Contr=0,0
English Units
Geom File=g01
Flow File=f01
Plan File=p01
Background Map Layer=Inundation Boundary (01pct Value_0)
BEGIN DESCRIPTION:
----------MODEL BY WOOD PLC 2021----------
Stream Name: Sugar Camp Run Tributary 1
Flood Zone: Enhanced Approximate
Pocahontas County, WV
HEC-RAS Version: RAS 6.1
Vertical Datum: NAVD88
Projection: NAD 1983 StatePlane West Virginia S FIPS 4702 (US Feet)
Terrain: 1-meter LIDAR (FEMA Region III 3DEP collected 2016-2018)
Land Use: 2019 NLCD
Hydrologic Method:
WV SIR2010-5033 regression equations
Model Notes:
Normal depth tie in to Sugar Camp Run
END DESCRIPTION:
DSS File=dss
DSS Export Rating Curves= 0
DSS Export Rating Curve Sorted= 0
DSS Export Volume Flow Curves= 0
DXF OffsetX= 0
DXF OffsetY= 0
DXF ScaleX= 0
DXF ScaleY= 0

--- SGRCMPRNT1.p01 (plan) ---

Plan Title=Floodplain
Program Version=6.10
Short Identifier=Floodplain
Geom File=g01
Flow File=f01
Subcritical Flow
K Sum by GR= 0
Std Step Tol= 0.01
Critical Tol= 0.01
Num of Std Step Trials= 20
Max Error Tol= 0.3
Flow Tol Ratio= 0.001
Split Flow NTrial= 30
Split Flow Tol= 0.02
Split Flow Ratio= 0.02
Log Output Level= 0
Friction Slope Method= 1
Unsteady Friction Slope Method= 2
Unsteady Bridges Friction Slope Method= 1
Parabolic Critical Depth
Global Vel Dist= 0 , 0 , 0
Global Log Level= 0
CheckData=True
Encroach Param=-1 ,0,0, 0
Computation Interval=0.1SEC
Output Interval=1SEC
Instantaneous Interval=Max Profile
Mapping Interval=1HOUR
Computation Time Step Use Courant=        0
Computation Time Step Use Time Series=    0
Computation Time Step Count To Double=0
Computation Time Step Max Doubling=0
Computation Time Step Max Halving=0
Computation Time Step Residence Courant=0
Run HTab= 0
Run UNet= 0
Run Sediment= 0
Run PostProcess= 0
Run WQNet= 0
Run RASMapper=-1
UNET Theta= 0
UNET Theta Warmup= 0
UNET ZTol= 0
UNET ZSATol= 0
UNET MxIter= 0
UNET Max Iter WO Improvement= 0
UNET MaxInSteps= 0
UNET DtIC= 0
UNET DtMin= 0
UNET MaxCRTS= 0
UNET WFStab= 0
UNET SFStab= 0
UNET WFX= 1
UNET SFX= 1
UNET Gravity=32.174
UNET 1D Methodology=Finite Difference
UNET DSS MLevel= 1
UNET Pardiso=0
UNET DZMax Abort= 0
UNET Use Existing IB Tables= 0
UNET Froude Reduction=False
UNET Froude Limit= 0
UNET Froude Power= 0
UNET D1 Cores= 0
UNET WindReference=Eulerian
UNET WindDragFormulation=Hsu (1988)
UNET D2 Coriolis=0
UNET D2 Cores= 0
UNET D2 Theta= 1
UNET D2 Theta Warmup= 1
UNET D2 Z Tol= 0.01
UNET D2 Volume Tol= 0.01
UNET D2 Max Iterations= 20
UNET D2 Equation= 0
UNET D2 RampUpFraction=0.1
UNET D2 TimeSlices= 1
UNET D2 Turbulence Formulation=Non-Conservative (original)
UNET D2 Eddy Viscosity=0.3
UNET D2 Transverse Eddy Viscosity=0.1
UNET D2 Smagorinsky Mixing=0
UNET D2 BCVolumeCheck=0
UNET D2 Cores=0
UNET D2 SolverType=PARDISO (Direct)
UNET D2 Minimum Iterations= 2147483647
UNET D2 Maximum Iterations= 2147483647
UNET D2 Restart Number= 10
UNET D2 Relaxation Coeff=1.3
UNET D2 SOR Precondition Iterations= 10
UNET D2 ILUT Maximum Fill= 8
UNET D2 ILUT Tolerance=1E-08
UNET D1D2 MaxIter= 0
UNET D1D2 ZTol=0.01
UNET D1D2 QTol=0.1
UNET D1D2 MinQTol=1
DSS File=dss
Write IC File= 0
Write IC File at Fixed DateTime=0
Write IC File at Sim End=0
Echo Input=False
Echo Parameters=False
Echo Output=False
Write Detailed= 0
HDF Write Warmup=0
HDF Write Time Slices=0
HDF Flush=0
HDF Compression= 1
HDF Chunk Size= 1
HDF Spatial Parts= 1
HDF Use Max Rows=0
HDF Fixed Rows= 1
Calibration Method= 0
Calibration Iterations= 20
Calibration Max Change=0.05
Calibration Tolerance=0.2
Calibration Maximum=1.5
Calibration Minimum=0.5
Calibration Optimization Method= 1
WQ AD Non Conservative
WQ ULTIMATE=-1
WQ Max Comp Step=1HOUR
WQ Output Interval=15MIN
WQ Output Selected Increments= 0
WQ Output face flow=0
WQ Output face velocity=0
WQ Output face area=0
WQ Output face dispersion=0
WQ Output cell volume=0
WQ Output cell surface area=0
WQ Output cell continuity=0
WQ Output cumulative cell continuity=0
WQ Output face conc=0
WQ Output face dconc_dx=0
WQ Output face courant=0
WQ Output face peclet=0
WQ Output face adv mass=0
WQ Output face disp mass=0
WQ Output cell mass=0
WQ Output cell source sink temp=0
WQ Output nsm pathways=0
WQ Output nsm derived pathways=0
WQ Create Restart=0
WQ Fixed Restart=0
WQ System Summary=0
WQ Write To DSS=0
Sorting and Armoring Iterations= 10
XS Update Threshold= 0.02
Bed Roughness Predictor= 0
Hydraulics Update Threshold= 0.02
Energy Slope Method= 1
Volume Change Method= 1
Sediment Retention Method= 0
Sediment TS Multiplier= 1
Warm Up Method= 0
XS Weighting Method= 0
Number of US Weighted Cross Sections= 1
Number of DS Weighted Cross Sections= 1
Upstream XS Weight=0
Main XS Weight=1
Downstream XS Weight=0
Number of DS XS's Weighted with US Boundary= 1
Upstream Boundary Weight= 1
Weight of XSs Associated with US Boundary= 0
Number of US XS's Weighted with DS Boundary= 1
Downstream Boundary Weight= 0.5
Weight of XSs Associated with DS Boundary= 0.5
Percentile Method= 0
Sediment Output Level= 3
Mass or Volume Output= 0
Output Increment Type= 1
Profile and TS Output Increment= 1
Transport Output Increment 1
XS Output Flag= 0
XS Output Increment= 10
Read HDF5 Sediment Hotstart= 0
Sediment Hotstart Type= 0
Write Gradation File= 0
Read Gradation Hotstart= 0
Write HDF5 File= 1
Write Binary Output= 1
Write DSS Sediment File= 0
DSS Sediment Output Type= 1
SV Curve= 0
Specific Gage Flag= 0
Subcell Erosion Methods= 0
Subcell Deposition Methods= 0
Advection Scheme= 1
Matrix Solver= 0
Implicit Weighting Factor= 1
Maximum Outer Loop Convergence Iterations= 5
Convergence Maximum Absolute= 0.001
Convergence RMSE= 0.0001
Grain Fractions Max Abs Error= 0.001
Max Subgrid Regions= 1
Max Subgrid Length Scale= 3.402823E+38
Initial Layer Thickness= 3.402823E+38
Min Layer Thickness= 3.402823E+38
Max Layer Thickness= 3.402823E+38
Number of Layers= 5

--- SGRCMPRNT1.f01 (steady flow) ---

Flow Title=Flow
Program Version=6.10
Number of Profiles= 6
Profile Names=01pct,10pct,04pct,02pct,0_2pct,01plus
River Rch & RM=SGRCMPRNT1,Main            ,1486
     434     227     304     367     610     643
River Rch & RM=SGRCMPRNT1,Main            ,465
     584     309     411     495     816     864
Boundary for River Rch & Prof#=SGRCMPRNT1,Main            , 1
Up Type= 0
Dn Type= 3
Dn Slope=0.00734
Boundary for River Rch & Prof#=SGRCMPRNT1,Main            , 2
Up Type= 0
Dn Type= 3
Dn Slope=0.00734
Boundary for River Rch & Prof#=SGRCMPRNT1,Main            , 3
Up Type= 0
Dn Type= 3
Dn Slope=0.00734
Boundary for River Rch & Prof#=SGRCMPRNT1,Main            , 4
Up Type= 0
Dn Type= 3
Dn Slope=0.00734
Boundary for River Rch & Prof#=SGRCMPRNT1,Main            , 5
Up Type= 0
Dn Type= 3
Dn Slope=0.00734
Boundary for River Rch & Prof#=SGRCMPRNT1,Main            , 6
Up Type= 0
Dn Type= 3
Dn Slope=0.00734
DSS Import GetInterval= 0
DSS Import GetPeak= 0
DSS Import FillOption= 0

--- SGRCMPRNT1.g01 (geometry) ---

Geom Title=Geometry
Program Version=6.10

River Reach=SGRCMPRNT1      ,Main
Reach XY= 30
     2291398.525       471246.63      2291390.45       471239.12
2291378.87524531471218.873718004     2291345.831      471114.712
2291310.43793278471034.1425664282291296.55210125  471009.3464387
2291269.27636075470973.887976048      2291223.45      470937.192
     2291209.921      470923.308     2291143.545      470839.197
2290996.76691701470678.814056081     2290985.459      470661.276
     2290950.035      470579.413     2290922.273      470527.313
     2290914.136       470430.34     2290894.838      470382.766
     2290886.257      470367.046      2290872.81        470354.2
     2290868.074      470352.362     2290838.654      470357.165
     2290827.625      470353.446     2290784.484      470318.374
     2290782.856      470275.458     2290779.217      470257.833
 2290745.8301044470147.9289614172290740.12699502 470138.50643288
2290709.37979664470096.600977019 2290689.0469719470081.971261659
2290682.84793997470079.9875714412290612.88390772470079.270861641

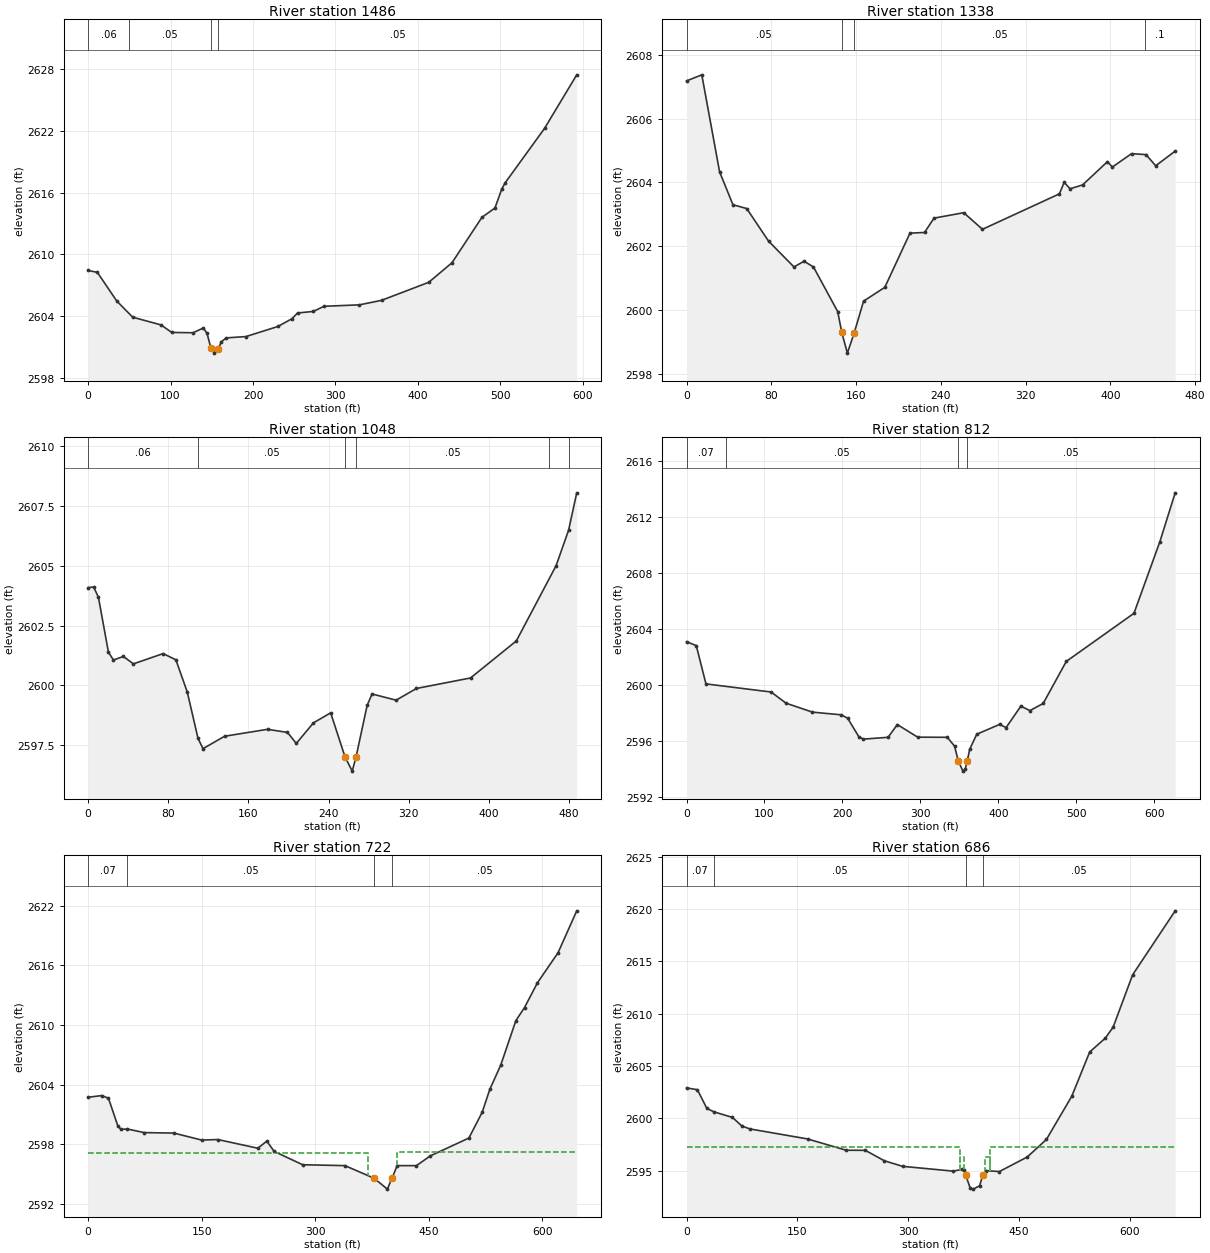
Type RM Length L Ch R = 1 ,1486    ,147.8,147.8,147.8
XS GIS Cut Line= 3
2291530.59990146471174.6739958592291169.95715605 471315.47671859
2291143.94358502471519.249691663
#Sta/Elev= 30
       0 2608.44    11.2 2608.26    34.7 2605.48    54.1  2603.9    88.5 2603.15
   101.4 2602.42   127.3 2602.39   139.7 2602.85   144.3 2602.33148.83222600.904
   152.9 2600.41158.03212600.847   161.5  2601.5   167.5 2601.89   191.5 2602.02
   230.2    2603   247.4 2603.76     254 2604.31   273.1 2604.46     286 2604.96
     329  2605.1   355.9 2605.54   413.1 2607.29   441.3 2609.19   477.6  2613.6
   493.4 2614.51   501.8 2616.37   505.8 2616.96   553.5 2622.24   592.6 2627.45
#Mann= 4 ,-1,0
       0     .06       0      50     .05       0148.8322    .045       0
158.0321     .05       0
Bank Sta=148.8322,158.0321
XS Rating Curve= 0 ,0
Exp/Cntr(USF)=0,0
Exp/Cntr=0.3,0.1

Type RM Length L Ch R = 1 ,1338    ,291.2,289.7,288.2
XS GIS Cut Line= 3
2291477.92242012471039.468460426 2291370.8115414471073.708823296
2291063.95916791471239.458335822
#Sta/Elev= 30
       0 2607.18    14.4 2607.37    31.2 2604.33    43.8  2603.3    56.8 2603.18
    77.4 2602.16   101.4 2601.35   110.9 2601.53   119.8 2601.35   142.7 2599.95
   146.5  2599.3   151.8 2598.65   158.3 2599.29   167.1 2600.28   187.1 2600.71
   210.9 2602.41   224.6 2602.43   233.6 2602.88   261.6 2603.05   279.3 2602.53
   351.9 2603.64   356.4    2604     362  2603.8   373.8 2603.92   397.3 2604.65
   401.9 2604.48     420  2604.9   433.7 2604.87   442.8 2604.52   461.2 2604.98
#Mann= 4 ,-1,0
       0     .05       0   146.5    .045       0   158.3     .05       0
  432.45      .1       0
Bank Sta=146.5,158.3
XS Rating Curve= 0 ,0
Exp/Cntr=0.3,0.1

Type RM Length L Ch R = 1 ,1048    ,234.8,236,236.5
XS GIS Cut Line= 2
2291372.56745745470711.1121600912290979.56810981470999.929414671
#Sta/Elev= 30
       0 2604.09     5.5 2604.12    10.3 2603.69    20.3 2601.39    25.3 2601.06
    35.2 2601.21    45.2  2600.9    74.9 2601.33    87.6 2601.07      99 2599.72
   109.7 2597.78   114.7 2597.35   136.2 2597.87   179.1 2598.16     199 2598.03
   207.8 2597.57   224.9 2598.43   242.1 2598.85   256.4 2597.01   263.6 2596.41
  267.47 2597.01   278.5 2599.16   283.4 2599.64   307.4 2599.38   327.7 2599.87
   381.7 2600.31   427.4 2601.86   467.1 2605.01   479.6  2606.5   487.7 2608.06
#Mann= 6 ,-1,0
       0     .06       0     110     .05       0   256.4    .045       0
  267.47     .05       0     460     .06       0     480     .05       0
Bank Sta=256.4,267.47
XS Rating Curve= 0 ,0
Exp/Cntr=0.3,0.1

Type RM Length L Ch R = 1 ,812     ,87.8,90.4,92.7
BEGIN DESCRIPTION:
structure xs 4
END DESCRIPTION:
XS GIS Cut Line= 4
 2291332.2886944470557.3914654782291136.32846383470607.171685342
2290941.15839547470729.6468294512290876.36509343470912.964464504
#Sta/Elev= 30
       0 2603.09    12.5 2602.81    24.9 2600.07   108.5 2599.49   127.7 2598.69
   161.6 2598.05   198.2 2597.86   206.7 2597.62   221.2 2596.28     227 2596.12
   258.6 2596.25   270.5 2597.16   296.6 2596.26   334.6 2596.25     344 2595.61
   348.5 2594.59   354.6 2593.83   357.5 2593.95   360.4 2594.59   363.3 2595.39
   372.4 2596.47   401.6 2597.17   410.1 2596.95     429 2598.48   440.6 2598.16
   457.6 2598.67   487.3 2601.68   574.1 2605.12   607.4 2610.25     627 2613.74
#Mann= 4 ,-1,0
       0     .07       0      50     .05       0   348.5    .045       0
   360.4     .05       0
Bank Sta=348.5,360.4
XS Rating Curve= 0 ,0
Exp/Cntr(USF)=0,0
Exp/Cntr=0.5,0.3

Type RM Length L Ch R = 1 ,722     ,35.6,35.7,35.7
BEGIN DESCRIPTION:
structure xs 3; 7.8 ft between structure and xs
END DESCRIPTION:
XS GIS Cut Line= 4
2291330.07773627470514.5737943262291256.10216236470493.697759714
2290851.24406781470654.7367170812290771.30537395 470760.98019698
#Sta/Elev= 30
       0 2602.74    18.1 2602.91    26.9 2602.64    39.4 2599.84    43.5 2599.51
    51.9 2599.55      74 2599.19   113.4 2599.14     150 2598.44   171.5 2598.49
   224.2 2597.62   236.1 2598.33   245.8  2597.3   283.4 2595.96   339.4 2595.87
   377.9  2594.6   395.3 2593.51  401.45 2594.61   408.3 2595.87   433.7 2595.87
   452.1 2596.85     503 2598.64   520.6 2601.23   530.6 2603.52   545.1 2605.97
   565.1 2610.44   576.5 2611.75   593.6 2614.24   620.8 2617.26   645.5 2621.47
#Mann= 4 ,-1,0
       0     .07       0    51.9     .05       0   377.9    .045       0
  401.45     .05       0
#XS Ineff= 2 , 0
             370 2597.17     408         2597.25
Permanent Ineff=
       F       F
Bank Sta=377.9,401.45
XS Rating Curve= 0 ,0
Exp/Cntr=0.5,0.3

Type RM Length L Ch R = 1 ,686     ,56,54.2,54.4
BEGIN DESCRIPTION:
structure xs 2; 7.8 ft between structure and xs
END DESCRIPTION:
XS GIS Cut Line= 4
2291313.96075996 470495.202650612291233.69179036470465.380308431
2290822.82877402470627.2171225392290735.17095473470728.790866139
#Sta/Elev= 30
       0  2602.9    14.7 2602.73    27.5 2600.94    37.2 2600.61    62.1 2600.08
    74.7 2599.27    85.6 2598.98   163.8 2598.02   216.1 2596.94     242 2596.93
   267.8 2595.93   292.5  2595.4   361.1 2594.94   373.5 2595.12   375.3 2595.09
  377.85 2594.55   383.9 2593.34   388.2 2593.22   396.8 2593.55   400.8 2594.54
   405.4 2594.99   423.4  2594.9   461.3  2596.3   487.1 2597.97   521.4  2602.1
   545.7 2606.34   566.8 2607.66   577.4 2608.71   603.8 2613.72   661.4 2619.84
#Mann= 4 ,-1,0
       0     .07       0    37.2     .05       0  377.85    .045       0
   400.8     .05       0
#XS Ineff= 4 ,-1
       0     370 2597.25     370     375  2596.3   403.5     411  2596.3
     411   661.4 2597.25
Permanent Ineff=
       F       F       F       F
Bank Sta=377.85,400.8
XS Rating Curve= 0 ,0
Exp/Cntr=0.5,0.3

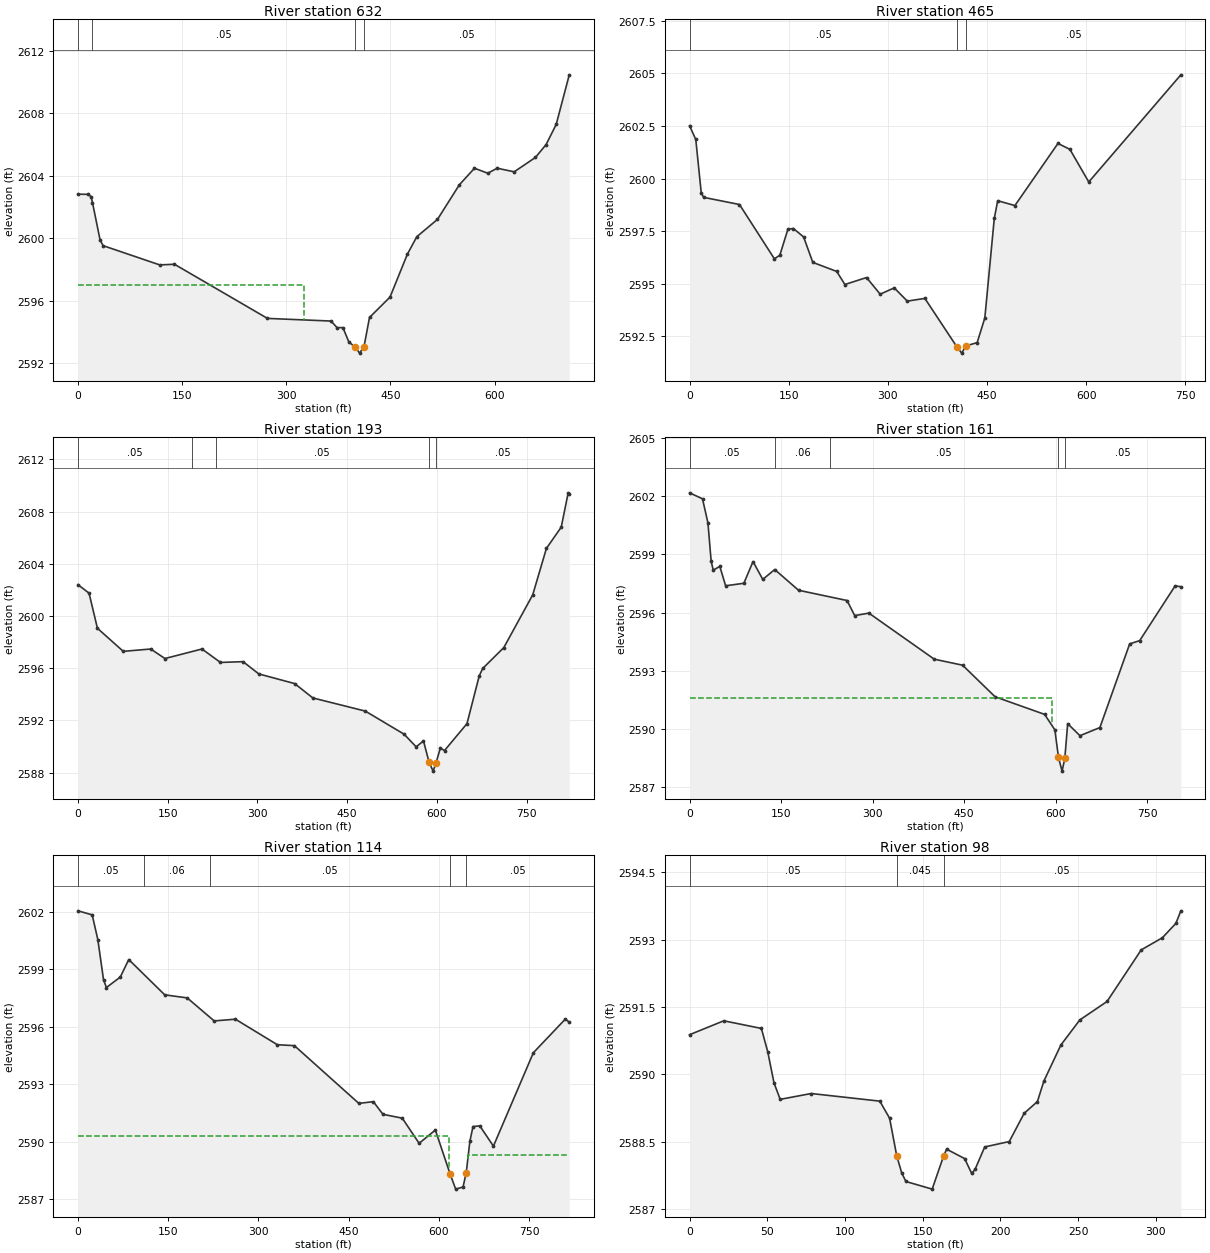
Type RM Length L Ch R = 1 ,632     ,170.3,166.6,164.2
BEGIN DESCRIPTION:
structure xs 1
END DESCRIPTION:
XS GIS Cut Line= 4
2291301.45285764470443.3349632942291236.93920148470415.868967881
2290748.10084586470593.628369924 2290686.6667735470693.604381247
#Sta/Elev= 30
       0 2602.82    14.4 2602.81    18.8 2602.67    20.9 2602.28    31.8  2599.9
    36.2 2599.53   117.7  2598.3     139 2598.34   272.9 2594.88   364.6 2594.71
   373.1 2594.29   381.6 2594.29   390.1 2593.38   399.5 2593.03   405.7 2592.66
     412 2593.08   419.9 2594.94   449.4 2596.24   474.4 2598.98     488  2600.1
   517.8 2601.21   549.3 2603.42   571.1 2604.48   590.2 2604.16   603.8 2604.48
   628.3 2604.25   658.9 2605.17   674.2 2605.99   688.8 2607.28   707.6 2610.45
#Mann= 4 ,-1,0
       0      .1       0    20.9     .05       0   399.5    .045       0
     412     .05       0
#XS Ineff= 2 , 0
             325    2597
Permanent Ineff=
       F       F
Bank Sta=399.5,412
XS Rating Curve= 0 ,0
Exp/Cntr(USF)=0,0
Exp/Cntr=0.3,0.1

Type RM Length L Ch R = 1 ,465     ,266.4,272.1,276.4
XS GIS Cut Line= 4
2291277.31567176470394.3351545652290956.48162905470321.713935437
2290829.66547028470410.5936364592290673.58404409470617.618305912
#Sta/Elev= 30
       0 2602.51     9.4 2601.86    17.6 2599.34    21.2 2599.11    75.5 2598.77
   128.3 2596.19   136.5 2596.36   148.8  2597.6     157 2597.63   172.5 2597.23
   186.4 2596.02   222.6 2595.59   234.9 2594.97   267.7  2595.3   288.3 2594.51
   309.6 2594.81   329.3 2594.18   355.9 2594.31   404.7 2591.99   411.7 2591.71
   417.8 2592.05     435 2592.21   446.6 2593.38   460.9 2598.11   466.1 2598.95
   492.1 2598.72   557.2 2601.67   575.3 2601.39   603.8 2599.84   743.1 2604.93
#Mann= 3 ,-1,0
       0     .05       0   404.7    .045       0   417.8     .05       0
Bank Sta=404.7,417.8
XS Rating Curve= 0 ,0
Exp/Cntr(USF)=0,0
Exp/Cntr=0.3,0.1

Type RM Length L Ch R = 1 ,193     ,35.3,31.7,28.9
BEGIN DESCRIPTION:
structure xs 4
END DESCRIPTION:
XS GIS Cut Line= 4
2291279.99166154470384.3166740182290897.67887929470153.565459988
 2290696.0737038470183.9146261912290596.35501485470322.653671688
#Sta/Elev= 30
       0  2602.4    18.5 2601.75    32.5 2599.06    75.7 2597.29   121.6 2597.47
   145.4 2596.74   207.3 2597.47   238.2 2596.44     276  2596.5   302.3 2595.56
   362.2 2594.82   392.6 2593.72   480.4 2592.71   545.2 2590.94   565.4 2589.97
   577.6 2590.43   586.9  2588.8   593.7 2588.11   598.7 2588.76   605.7 2589.87
   612.8 2589.69   650.3 2591.75   670.8 2595.41   676.6 2595.98   711.9 2597.58
   760.2 2601.62   783.1 2605.18   807.9 2606.81   819.5 2609.44   821.3 2609.36
#Mann= 5 ,-1,0
       0     .05       0     190     .06       0     230     .05       0
   586.9    .045       0   598.7     .05       0
Bank Sta=586.9,598.7
XS Rating Curve= 0 ,0
Exp/Cntr(USF)=0,0
Exp/Cntr=0.5,0.3

Type RM Length L Ch R = 1 ,161     ,39.7,47.5,47.1
BEGIN DESCRIPTION:
structure xs 3; 10.7 ft between structure and xs
END DESCRIPTION:
XS GIS Cut Line= 6
2291278.04064371 470360.904460092290894.44061008470117.373770529
2290767.27277164470128.6179526152290752.25927126470141.187859565
2290737.43664203470148.5991741822290554.09511213470186.144644365
#Sta/Elev= 30
       0 2602.18    21.2 2601.87    30.1 2600.63    35.4 2598.64    38.8 2598.19
    49.6 2598.38    59.1 2597.38      89 2597.51     104 2598.63     120 2597.71
   139.6 2598.22   178.6 2597.15   258.1 2596.62   270.7 2595.84   293.9 2595.97
   401.1 2593.59   447.5 2593.28   500.8 2591.65     582 2590.74   598.8 2589.94
   604.7 2588.52   610.6 2587.81615.08292588.467   619.8 2590.26   639.9 2589.64
   672.6 2590.06   721.4 2594.38   737.9 2594.55     796 2597.38   805.3 2597.33
#Mann= 5 ,-1,0
       0     .05       0     140     .06       0     230     .05       0
   604.7    .045       0615.0829     .05       0
#XS Ineff= 2 , 0
             594  2591.6     626          2589.9
Permanent Ineff=
       F       F
Bank Sta=604.7,615.0829
XS Rating Curve= 0 ,0
Exp/Cntr=0.5,0.3

Type RM Length L Ch R = 1 ,114     ,15.7,15.7,15.7
BEGIN DESCRIPTION:
structure xs 2; 8 ft between structure and xs
END DESCRIPTION:
XS GIS Cut Line= 6
2291276.08962588470342.3697907312290890.08715714470097.727833837
2290723.15630411470103.5889951682290707.79138356470110.096490929
2290672.08986221 470145.881519522290549.90123221  470172.5194233
#Sta/Elev= 30
       0 2602.04    23.6 2601.83      33 2600.54    42.5 2598.44    47.3 2598.04
    70.4 2598.59    84.4  2599.5   144.2 2597.66   181.6  2597.5   226.4  2596.3
   261.7 2596.39   331.4 2595.06   359.8 2595.01   466.9    2592     491 2592.09
     507 2591.43   539.1 2591.23   567.1 2589.92   594.1 2590.61   618.4 2588.34
   627.9 2587.53   640.1 2587.64   645.4 2588.38   651.5 2590.03   656.7 2590.79
     668 2590.83   690.6 2589.77     757 2594.64   810.3  2596.4   816.7 2596.23
#Mann= 5 ,-1,0
       0     .05       0     110     .06       0     220     .05       0
   618.4    .045       0   645.4     .05       0
#XS Ineff= 2 , 0
             616  2590.3     648          2589.3
Permanent Ineff=
       F       F
Bank Sta=618.4,645.4
XS Rating Curve= 0 ,0
Exp/Cntr=0.5,0.3

Type RM Length L Ch R = 1 ,98      ,,,
BEGIN DESCRIPTION:
structure xs 1
END DESCRIPTION:
XS GIS Cut Line= 3
2290850.32376078 470079.908371522290724.86480609470088.203178441
2290544.97118099470150.414230351
#Sta/Elev= 30
       0 2590.88      22 2591.19    46.2 2591.02    50.3  2590.5    54.3 2589.81
    58.3 2589.44    78.3 2589.57   122.4  2589.4   128.7 2589.02   133.3 2588.18
   136.5  2587.8   139.2 2587.61   156.1 2587.44  163.47 2588.18   165.4 2588.33
     177 2588.12   181.5 2587.79   183.7 2587.88   189.9 2588.38   205.7  2588.5
   215.3 2589.13   223.8 2589.39     228 2589.85   238.9 2590.65   251.1 2591.21
   268.6 2591.62   290.6 2592.77   304.2 2593.04   312.9 2593.36   316.1 2593.64
#Mann= 3 ,0,0
       0     .05       0   133.3    .045       0  163.47     .05       0
Bank Sta=133.3,163.47
XS Rating Curve= 0 ,0
Exp/Cntr(USF)=0,0
Exp/Cntr=0.3,0.1
LCMann Table=0

Chan Stop Cuts=-1
Use User Specified Reach Order=0
Composite Channel Slope=5